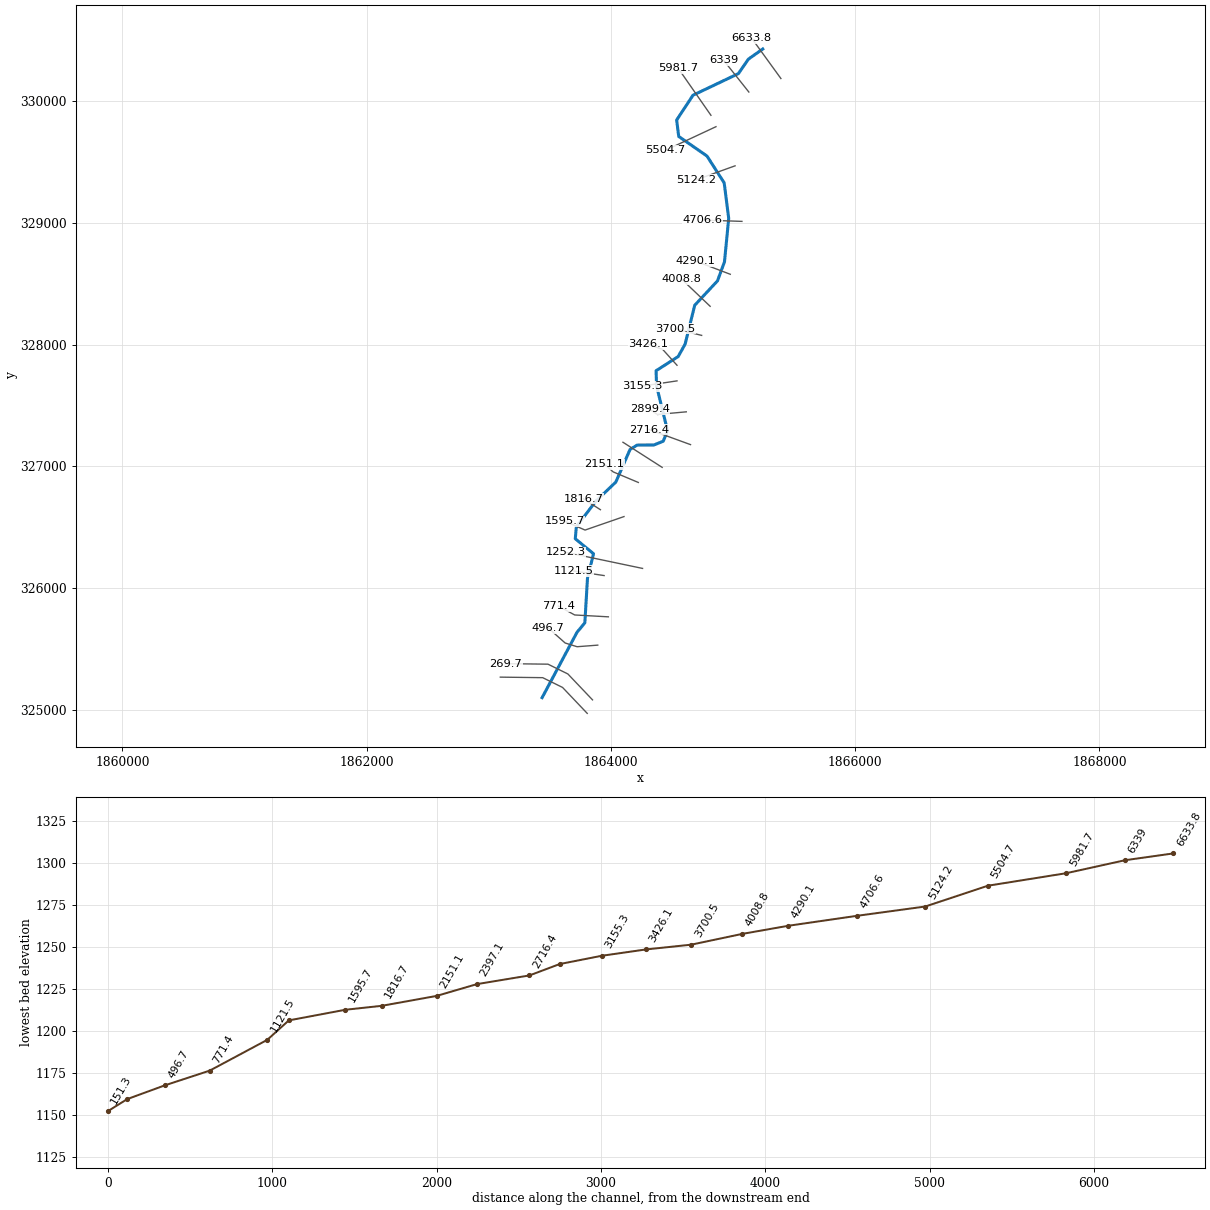
--- COOKSRN.prj (project) ---

Proj Title=COOKSRN
Current Plan=p01
Geom File=g01
Flow File=f01
Plan File=p01
DSS Export Rating Curves=0
DSS Export Rating Curve Sorted=0
DSS Export Volume Flow Curves=0
DXF OffsetX=0
DXF OffsetY=0
DXF ScaleX=0
DXF ScaleY=0

--- COOKSRN.p01 (plan) ---

Plan Title=Floodplain
Program Version=4.00
Geom File=g01
Flow File=f01
K Sum by GR=0
Std Step Tol=0.01
Critical Tol=0.01
Num of Std Step Trials=20
Max Error Tol=0.3
Flow Tol Ratio=0.001
Split Flow NTrial=30
Split Flow Tol=0.02
Split Flow Ratio=0.02
Log Output Level=0
Friction Slope Method=1
Unsteady Friction Slope Method=2
Unsteady Bridges Friction Slope Method=1
Global Log Level=0
CheckData=False
Run HTab=0
Run UNet=0
Run PostProcess=0
UNET Theta=0
UNET Theta Warmup=0
UNET ZTol=0
UNET ZSATol=0
UNET MxIter=0
UNET MaxInSteps=0
UNET DtIC=0
UNET DtMin=0
UNET MaxCRTS=0
UNET WFStab=0
UNET SFStab=0
UNET WFX=0
UNET SFX=0
UNET DSS MLevel=0
UNET DZMax Abort=0
UNET Convert EG Bridges=0
UNET Use Existing IB Tables=0
UNET Froude Limit=0
UNET Froude Power=0
Write IC File=0
Echo Input=False
Echo Output=False
Write Detailed=0

--- COOKSRN.f01 (steady flow) ---

Flow Title=NFF Regression Equation
Program Version=4.10
Number of Profiles= 1
Profile Names=P100yr
River Rch & RM=COOKSRN,Main            ,6633.8
595.4867
River Rch & RM=COOKSRN,Main            ,3155.3
657.4267
River Rch & RM=COOKSRN,Main            ,1816.7
714.9054
River Rch & RM=COOKSRN,Main            ,269.7
773.1442
Boundary for River Rch & Prof#=COOKSRN,Main            , 1
Up Type= 0
Dn Type= 3
Dn Slope=0.01745
DSS Import GetInterval= 0
DSS Import GetPeak= 0
DSS Import FillOption= 0

--- COOKSRN.g01 (geometry) ---

Geom Title=USGS 10m DEM
Program Version=4.10

River Reach=COOKSRN         ,Main
Reach XY= 30
     1865243.488      330424.864     1865125.687      330341.512
     1865043.835       330222.78     1864672.307      330045.697
     1864538.389      329841.978       1864555.6      329707.476
     1864786.789      329546.676     1864927.515      329326.947
     1864964.741      329035.392     1864930.018      328678.621
     1864872.753      328522.382     1864686.409       328322.39
     1864607.608      328003.064     1864550.779        327901.6
     1864370.224       327785.28     1864373.696      327662.017
     1864463.639      327293.707     1864428.767      327207.198
     1864351.893      327176.017      1864215.71      327175.558
     1864156.682        327139.1     1864040.362      326871.739
     1863875.432      326713.753     1863717.345       326505.01
     1863708.361       326407.02      1863857.97      326283.656
     1863808.491      326084.003     1863786.789      325716.815
     1863722.651      325639.382     1863436.921      325103.271

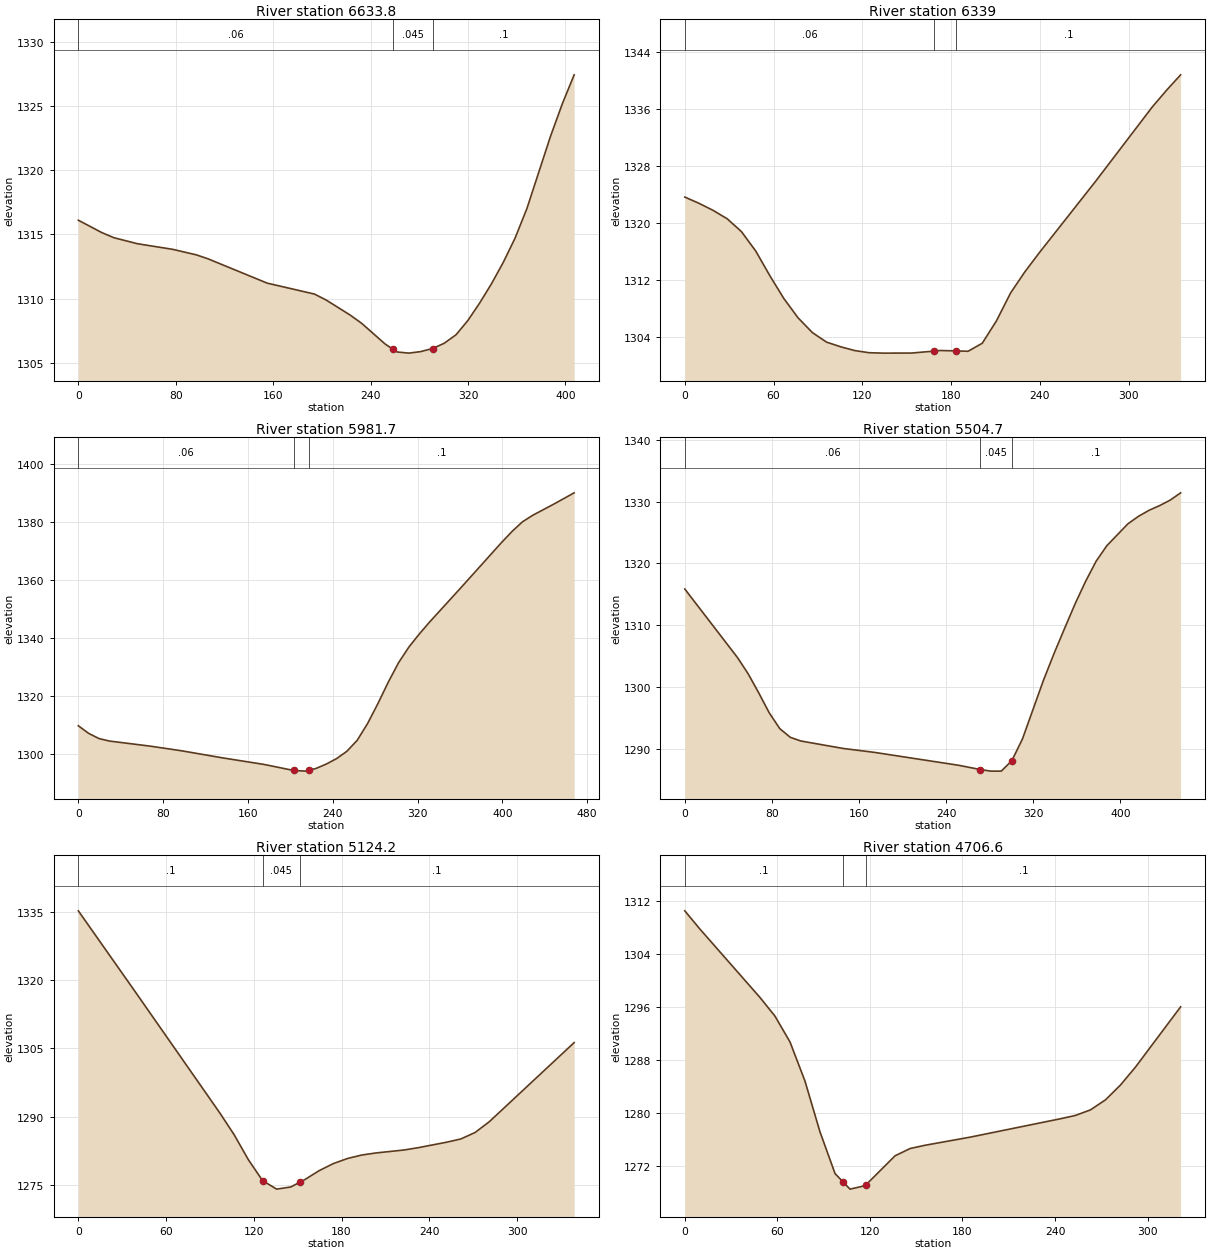
Type RM Length L Ch R = 1 ,6633.8  ,293.8,294.7,296
XS GIS Cut Line= 2
     1865392.149      330182.527     1865153.434      330512.388
#Sta/Elev= 29
       0  1316.1    19.4 1315.13    29.1 1314.74    48.5 1314.27    77.6 1313.83
      97  1313.4   106.6 1313.09   155.1  1311.2   193.9 1310.35   203.6 1309.88
     223 1308.73   232.7 1308.07   252.1 1306.45  258.451306.051   261.8 1305.84
   271.4 1305.75   281.2 1305.87     291 1306.11   300.5 1306.52   310.2 1307.18
   319.9 1308.29   329.6 1309.65   339.3 1311.15     349 1312.82   358.7 1314.71
   368.4 1317.01   387.8 1322.64   397.5 1325.17   407.2 1327.42
#Mann= 3 , 0 , 0
       0     .06       0  258.45    .045       0     291      .1       0
Bank Sta=258.45,291
XS Rating Curve= 0 ,0
Exp/Cntr=0.3,0.1

Type RM Length L Ch R = 1 ,6339    ,358.4,357.3,355.8
XS GIS Cut Line= 2
     1865129.563       330071.85     1864921.229      330334.437
#Sta/Elev= 29
       0 1323.64     9.6 1322.76    19.2 1321.76    28.7 1320.58    38.3 1318.78
    47.9 1316.07    57.5 1312.58      67 1309.36    76.6 1306.65    86.2 1304.59
    95.8 1303.24   105.4 1302.58   114.9 1302.05   124.5 1301.75   134.1 1301.69
   153.2  1301.7   168.4 1301.97   172.4 1302.06   183.4    1302   191.5 1301.95
   201.1 1303.08   210.7 1306.23   220.3 1310.17   229.8 1313.09   239.4 1315.74
   277.7 1325.85     316  1336.3   325.6 1338.64   335.2 1340.83
#Mann= 3 , 0 , 0
       0     .06       0   168.4    .045       0   183.4      .1       0
Bank Sta=168.4,183.4
XS Rating Curve= 0 ,0
Exp/Cntr=0.3,0.1

Type RM Length L Ch R = 1 ,5981.7  ,446.1,477,508.9
XS GIS Cut Line= 2
     1864819.233      329880.878     1864552.306      330264.992
#Sta/Elev= 30
       0 1309.64     9.7 1307.01    19.5 1305.21    29.2 1304.36    68.2 1302.57
    97.4 1300.99   136.4 1298.52   175.4 1296.26   203.1 1294.19   214.4 1293.96
   218.1  1294.3   224.1 1294.86   233.9 1296.39   243.6 1298.27   253.4 1300.82
   263.1 1304.61   272.9  1310.4   282.6 1317.26   292.4 1324.67   302.1 1331.39
   311.8 1336.78   321.6 1341.29   331.3 1345.42   360.6 1357.18   399.5 1373.02
   409.3 1376.79     419 1380.08   428.8 1382.36   448.3 1386.14   467.8  1390.1
#Mann= 3 , 0 , 0
       0     .06       0   203.1    .045       0   218.1      .1       0
Bank Sta=203.1,218.1
XS Rating Curve= 0 ,0
Exp/Cntr=0.3,0.1

Type RM Length L Ch R = 1 ,5504.7  ,381.1,380.5,378.7
XS GIS Cut Line= 2
     1864860.465      329787.562     1864448.139       329594.42
#Sta/Elev= 29
       0 1315.88    48.4 1304.82    58.1 1302.23    67.8 1299.16    77.5 1295.92
    87.2 1293.36    96.9 1291.95   106.6 1291.36   145.3 1290.16   174.4 1289.52
   251.9 1287.43   271.2 1286.76   280.9  1286.5   290.6  1286.5   300.3 1288.18
     310 1291.67   329.4 1301.18   339.1 1305.49   348.8 1309.54   358.4 1313.49
   368.1 1317.14   377.8 1320.39   387.5 1322.86   406.9  1326.4   416.6 1327.61
   426.3 1328.58     436 1329.34   445.6 1330.21   455.3  1331.4
#Mann= 3 , 0 , 0
       0     .06       0   271.2    .045       0   300.3      .1       0
Bank Sta=271.2,300.3
XS Rating Curve= 0 ,0
Exp/Cntr=0.3,0.1

Type RM Length L Ch R = 1 ,5124.2  ,426,417.6,408.9
XS GIS Cut Line= 2
     1865016.715      329466.381     1864697.705      329351.364
#Sta/Elev= 22
       0 1335.15    38.8 1317.46    96.9 1290.77   106.6 1286.04   116.3 1280.58
     126    1276   135.6 1274.13   145.3  1274.6   151.7 1275.68     155 1276.24
   164.7 1278.18   174.4 1279.73   184.1 1280.85   193.8  1281.6   203.5 1282.06
   222.8 1282.71   232.5 1283.22   251.9 1284.42   261.6 1285.13   271.3 1286.54
     281 1288.89   339.1 1306.26
#Mann= 3 , 0 , 0
       0      .1       0     126    .045       0   151.7      .1       0
Bank Sta=126,151.7
XS Rating Curve= 0 ,0
Exp/Cntr=0.3,0.1

Type RM Length L Ch R = 1 ,4706.6  ,423.8,416.5,408.9
XS GIS Cut Line= 2
     1865073.139      329010.652     1864751.958      329021.503
#Sta/Elev= 23
       0 1310.48     9.7 1307.76    48.7 1297.44    58.4 1294.64    68.2 1290.73
    77.9 1284.84    87.6 1277.21    97.4  1270.9   102.4 1269.69   107.1 1268.56
   116.9 1269.08   117.4  1269.2   136.3 1273.58   146.1 1274.68   155.8 1275.17
     185 1276.39   243.5 1279.16   253.2 1279.66   262.9 1280.49   272.7 1282.01
   282.4 1284.24   292.2 1286.96   321.4 1296.02
#Mann= 3 , 0 , 0
       0      .1       0   102.4    .045       0   117.4      .1       0
Bank Sta=102.4,117.4
XS Rating Curve= 0 ,0
Exp/Cntr=0.3,0.1

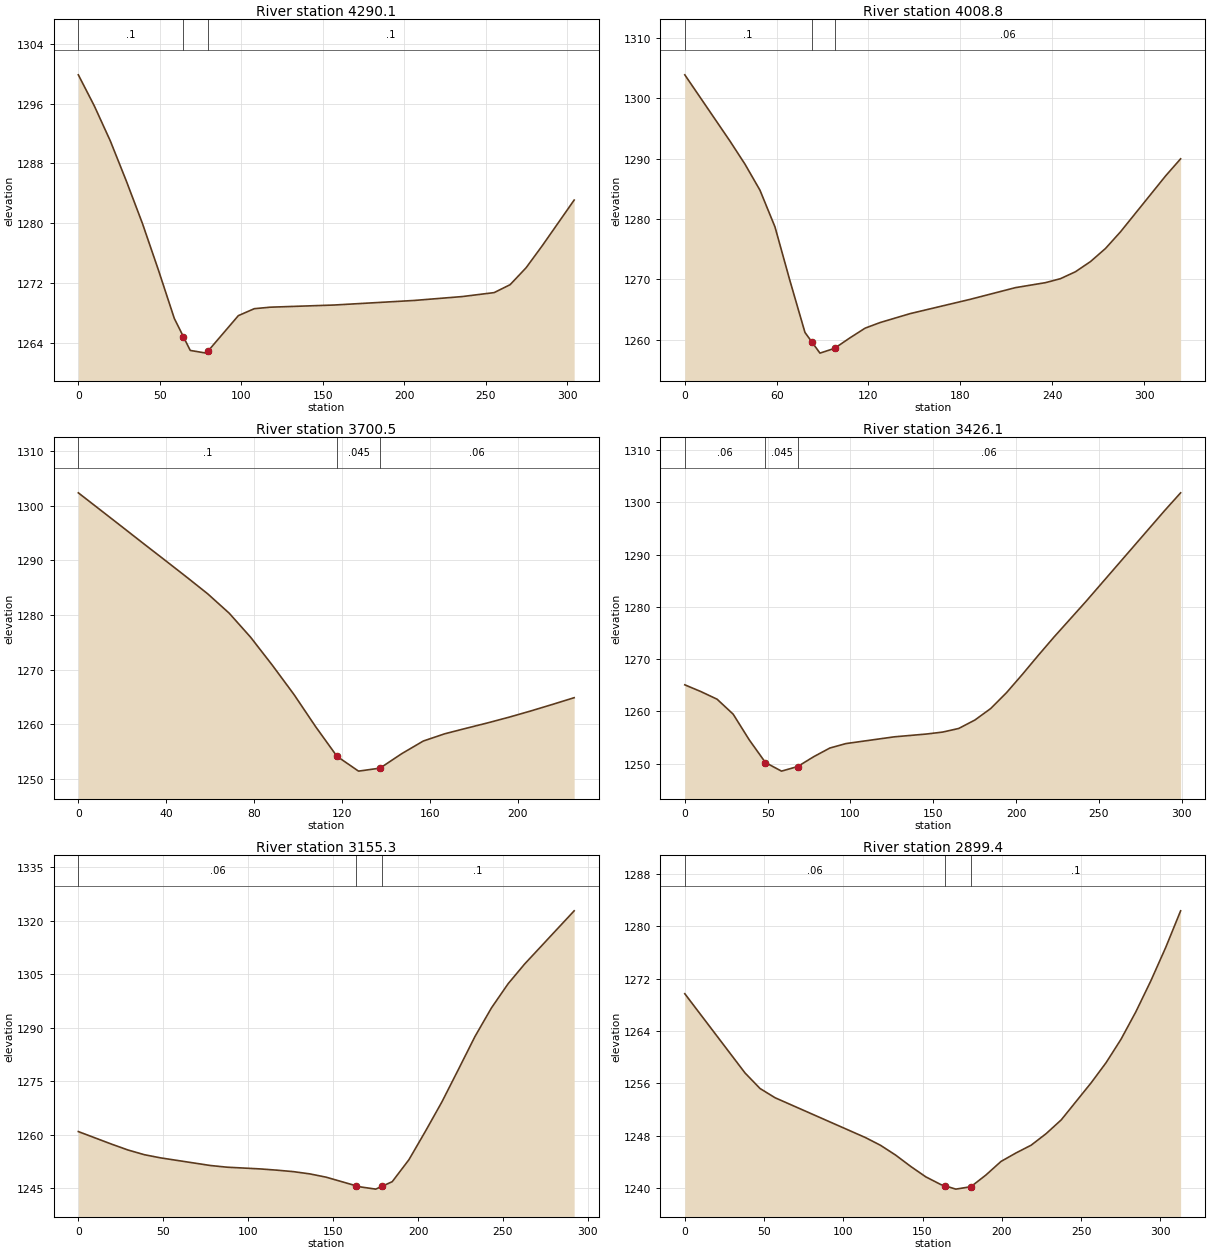
Type RM Length L Ch R = 1 ,4290.1  ,290.2,281.3,272.2
XS GIS Cut Line= 2
     1864977.653      328576.624     1864693.365      328685.131
#Sta/Elev= 22
       0 1299.85     9.8  1295.7    19.6 1291.03    29.4 1285.69    39.3 1280.01
    49.1 1273.79    58.9 1267.29    64.5 1264.84    68.7 1263.01    78.5 1262.65
    79.5  1262.9    98.2 1267.66     108 1268.59   117.8 1268.79     157 1269.08
   206.1 1269.69   235.6 1270.21   255.2 1270.74     265  1271.8   274.8 1274.06
   284.7    1277   304.3 1283.11
#Mann= 3 , 0 , 0
       0      .1       0    64.5    .045       0    79.5      .1       0
Bank Sta=64.5,79.5
XS Rating Curve= 0 ,0
Exp/Cntr=0.3,0.1

Type RM Length L Ch R = 1 ,4008.8  ,296.2,308.3,320.4
XS GIS Cut Line= 2
     1864812.722      328314.038     1864578.347      328537.562
#Sta/Elev= 24
       0 1303.91    29.4 1292.97    39.3 1289.11    49.1 1284.79    58.9 1278.71
    68.7 1269.77    78.5 1261.21    82.8  1259.7    88.3 1257.78    97.8 1258.57
     108 1260.33   117.8 1261.92   127.6 1262.85   147.2 1264.33   186.5  1266.7
   215.9 1268.63   235.6 1269.46   245.4 1270.12   255.2 1271.27     265 1272.95
   274.8 1275.12   284.6 1277.88   314.1 1287.16   323.9 1289.99
#Mann= 3 , 0 , 0
       0      .1       0    82.8    .045       0    97.8     .06       0
Bank Sta=82.8,97.8
XS Rating Curve= 0 ,0
Exp/Cntr=0.3,0.1

Type RM Length L Ch R = 1 ,3700.5  ,288,274.4,260.7
XS GIS Cut Line= 2
     1864743.278      328075.322     1864524.094      328129.576
#Sta/Elev= 26
       0 1302.35     9.8 1299.29    19.6 1296.23    29.4 1293.15    39.3 1290.07
    49.1    1287    58.9 1283.87    68.7 1280.32    78.5  1275.9    88.4 1270.77
    98.2 1265.44     108 1259.59   115.5  1255.4   117.8 1254.12   127.6 1251.41
   130.5 1251.57   137.4 1251.96   147.3 1254.61   157.1 1256.92   166.9 1258.25
   176.7 1259.26   186.5 1260.25   196.4 1261.31   206.2 1262.44     216 1263.63
   225.8 1264.85
#Mann= 3 , 0 , 0
       0      .1       0   117.8    .045       0   137.4     .06       0
Bank Sta=117.8,137.4
XS Rating Curve= 0 ,0
Exp/Cntr=0.3,0.1

Type RM Length L Ch R = 1 ,3426.1  ,247.8,270.8,293.9
XS GIS Cut Line= 3
     1864541.455      327830.097     1864424.267      327960.305
      1864307.08      328001.538
#Sta/Elev= 24
       0 1265.09     9.7  1263.8    19.5 1262.34    29.2 1259.48    38.9 1254.57
    48.7 1250.22    58.4 1248.58    68.1 1249.45    77.9 1251.35    87.6    1253
    97.3 1253.85   126.5 1255.14     146 1255.68   155.7 1256.05   165.4 1256.74
   175.2 1258.36   184.7 1260.55   194.3  1263.6   203.8 1267.07   213.4 1270.71
     223 1274.25   242.1 1280.99   289.8 1298.44   299.4 1301.82
#Mann= 3 , 0 , 0
       0     .06       0    48.7    .045       0    68.1     .06       0
Bank Sta=48.7,68.1
XS Rating Curve= 0 ,0
Exp/Cntr=0.3,0.1

Type RM Length L Ch R = 1 ,3155.3  ,257.2,255.9,254.6
XS GIS Cut Line= 2
     1864541.455      327702.058     1864252.827      327658.656
#Sta/Elev= 26
       0 1260.92    19.5 1257.41    29.2 1255.76    38.9 1254.43    48.6 1253.53
    77.8  1251.4    87.6 1250.93     107 1250.45   116.8  1250.1   126.5 1249.69
   136.2 1249.06   145.9 1248.13   163.7 1245.69   165.4 1245.45   175.1 1244.78
   178.7 1245.56   184.8 1246.87   194.6 1253.01   204.3 1260.97     214  1269.2
   223.8 1278.38   233.5 1287.57   243.2 1295.59     253 1302.36   262.7 1307.88
   291.9 1322.82
#Mann= 3 , 0 , 0
       0     .06       0   163.7    .045       0   178.7      .1       0
Bank Sta=163.7,178.7
XS Rating Curve= 0 ,0
Exp/Cntr=0.3,0.1

Type RM Length L Ch R = 1 ,2899.4  ,193.1,183,172.8
XS GIS Cut Line= 3
      1864617.41      327448.152     1864380.865      327426.451
     1864317.931      327467.683
#Sta/Elev= 26
       0 1269.68      38 1257.58    47.5  1255.2      57 1253.79     114 1247.71
   123.5 1246.53     133 1245.04   142.5 1243.31     152 1241.72   161.5 1240.54
   164.2 1240.34     171 1239.84   180.5 1240.21     190    1242   199.5 1244.07
     209 1245.37   218.5 1246.55     228 1248.32   237.5 1250.42   256.4 1256.09
   265.8 1259.16   275.2 1262.73   284.6 1266.94     294 1271.64   303.4 1276.75
   312.8 1282.34
#Mann= 3 , 0 , 0
       0     .06       0   164.2    .045       0   180.5      .1       0
Bank Sta=164.2,180.5
XS Rating Curve= 0 ,0
Exp/Cntr=0.3,0.1

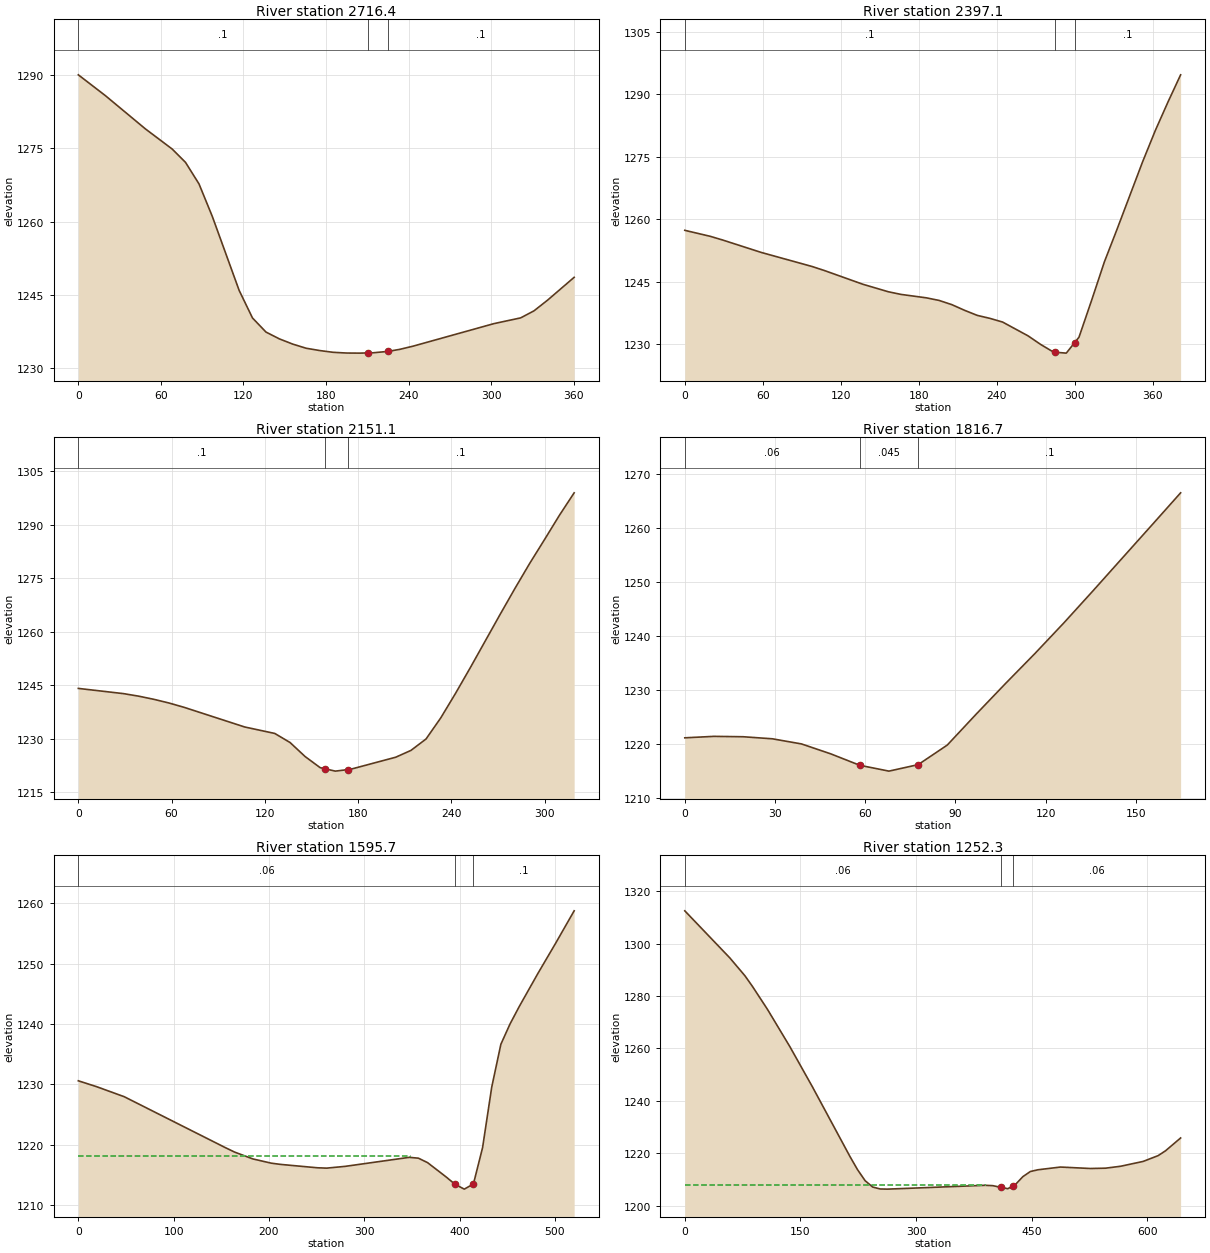
Type RM Length L Ch R = 1 ,2716.4  ,323,319.3,314.9
XS GIS Cut Line= 2
     1864652.132      327179.055      1864313.59      327302.753
#Sta/Elev= 27
       0 1290.03    19.5 1285.81    48.7 1278.98    68.2 1274.85    77.9 1272.12
    87.7 1267.72    97.4 1261.05   116.9 1245.92   126.6 1240.28   136.4  1237.4
   146.1 1236.01   155.9 1234.93   165.6 1234.09   175.4 1233.62   185.1 1233.26
   194.8 1233.11   204.6 1233.09   210.3 1233.13   214.3 1233.16   225.3 1233.45
   233.8 1233.87   243.5 1234.53     302 1239.12   321.5  1240.3   331.2 1241.74
     341 1243.91   360.4  1248.6
#Mann= 3 , 0 , 0
       0      .1       0   210.3    .045       0   225.3      .1       0
Bank Sta=210.3,225.3
XS Rating Curve= 0 ,0
Exp/Cntr=0.3,0.1

Type RM Length L Ch R = 1 ,2397.1  ,243,245.9,249.6
XS GIS Cut Line= 2
     1864419.927      326992.423     1864098.747      327198.586
#Sta/Elev= 30
       0 1257.37    19.6 1255.93    29.4 1255.02    58.7 1252.08    97.9  1248.7
   107.6 1247.71     137 1244.44   156.6 1242.64   166.4    1242   185.9 1241.18
   195.7 1240.56   205.5 1239.55   215.3 1238.19   225.1 1236.97   234.9 1236.25
   244.6 1235.37   264.2 1232.06     274 1229.98   283.8 1228.16   285.1 1228.13
   293.6 1227.92   300.1 1230.46   303.4 1231.75   313.2 1240.68   322.9 1249.78
   332.7 1257.65   352.3 1273.77   362.1 1281.29   371.9 1288.16   381.6 1294.66
#Mann= 3 , 0 , 0
       0      .1       0   285.1    .045       0   300.1      .1       0
Bank Sta=285.1,300.1
XS Rating Curve= 0 ,0
Exp/Cntr=0.3,0.1

Type RM Length L Ch R = 1 ,2151.1  ,338.3,334.4,330.5
XS GIS Cut Line= 3
     1864224.615      326868.725     1864018.452      326955.531
     1863946.837      327018.465
#Sta/Elev= 27
       0 1244.07    29.2  1242.6    38.9 1241.89    48.6 1241.01    58.4 1239.97
    68.1 1238.76     107 1233.26   126.4 1231.44   136.2 1228.91   145.9 1224.97
   155.6 1221.85   158.6 1221.55   165.3 1220.88   173.6 1221.31   175.1 1221.39
   204.2 1224.78     214 1226.69   223.7 1229.89   233.2 1235.82   242.8 1242.77
   252.3 1249.97   271.4 1264.84   280.9 1272.09   290.4 1279.12     300 1285.84
   309.5 1292.59     319  1298.9
#Mann= 3 , 0 , 0
       0      .1       0   158.6    .045       0   173.6      .1       0
Bank Sta=158.6,173.6
XS Rating Curve= 0 ,0
Exp/Cntr=0.3,0.1

Type RM Length L Ch R = 1 ,1816.7  ,217.4,221,224.4
XS GIS Cut Line= 2
     1863914.285      326645.201     1863775.396      326734.176
#Sta/Elev= 20
       0 1221.15     9.7 1221.42    19.4 1221.35    29.1 1220.97    38.8 1220.02
    48.5 1218.19    58.2 1216.06    66.3 1215.16    67.9 1214.98    77.6 1216.18
    81.3 1217.56    87.3 1219.81      97 1225.59   106.7 1231.23   116.4 1236.74
   126.1 1242.46   135.8 1248.41   145.5 1254.45   155.2 1260.48   164.9 1266.54
#Mann= 3 , 0 , 0
       0     .06       0    58.2    .045       0    77.6      .1       0
Bank Sta=58.2,77.6
XS Rating Curve= 0 ,0
Exp/Cntr=0.3,0.1

Type RM Length L Ch R = 1 ,1595.7  ,339.2,343.4,347.3
XS GIS Cut Line= 3
     1864107.427      326588.777     1863788.417        326478.1
     1863621.316      326551.885
#Sta/Elev= 26
       0  1230.6    19.3 1229.62    48.2 1227.96   154.4 1219.51     164 1218.78
   183.3 1217.64   202.6 1216.94   212.2 1216.74   250.8 1216.18   260.5 1216.12
   279.8 1216.41   347.3 1217.91   356.9 1217.77   366.5 1217.03   385.7 1214.69
   395.4 1213.43     405 1212.64   414.6 1213.49   424.2 1219.52   433.8 1229.55
   443.4 1236.66     453 1240.02   462.6 1242.89   481.9  1248.3   501.1 1253.47
   520.3 1258.78
#Mann= 3 , 0 , 0
       0     .06       0   395.4    .045       0   414.6      .1       0
#XS Ineff= 2 , 0
          348.17 1218.06
Permanent Ineff=
       F       F
Bank Sta=395.4,414.6
XS Rating Curve= 0 ,0
Exp/Cntr=0.3,0.1

Type RM Length L Ch R = 1 ,1252.3  ,129.4,130.9,132
XS GIS Cut Line= 2
     1864259.337       326163.43     1863629.997      326295.808
#Sta/Elev= 30
       0 1312.47    58.5 1294.48      78  1287.7    87.7 1283.66   107.2  1274.9
   136.4  1260.6   165.6  1245.3   214.4 1218.66   224.1 1213.71   233.9 1209.53
   243.6 1207.12   253.4 1206.37   263.1 1206.31   389.8 1207.77   399.5 1207.63
   410.3 1206.97     419 1206.47   425.3 1207.48   428.7 1208.02   438.5 1211.07
   448.2 1213.03     458 1213.69   487.2 1214.73   526.2 1214.18   545.7  1214.3
   565.2 1215.03   594.4 1216.87   613.9 1219.08   623.6 1220.95   643.1 1225.83
#Mann= 3 , 0 , 0
       0     .06       0   410.3    .045       0   425.3     .06       0
#XS Ineff= 2 , 0
           390.2 1207.93
Permanent Ineff=
       F       F
Bank Sta=410.3,425.3
XS Rating Curve= 0 ,0
Exp/Cntr=0.3,0.1

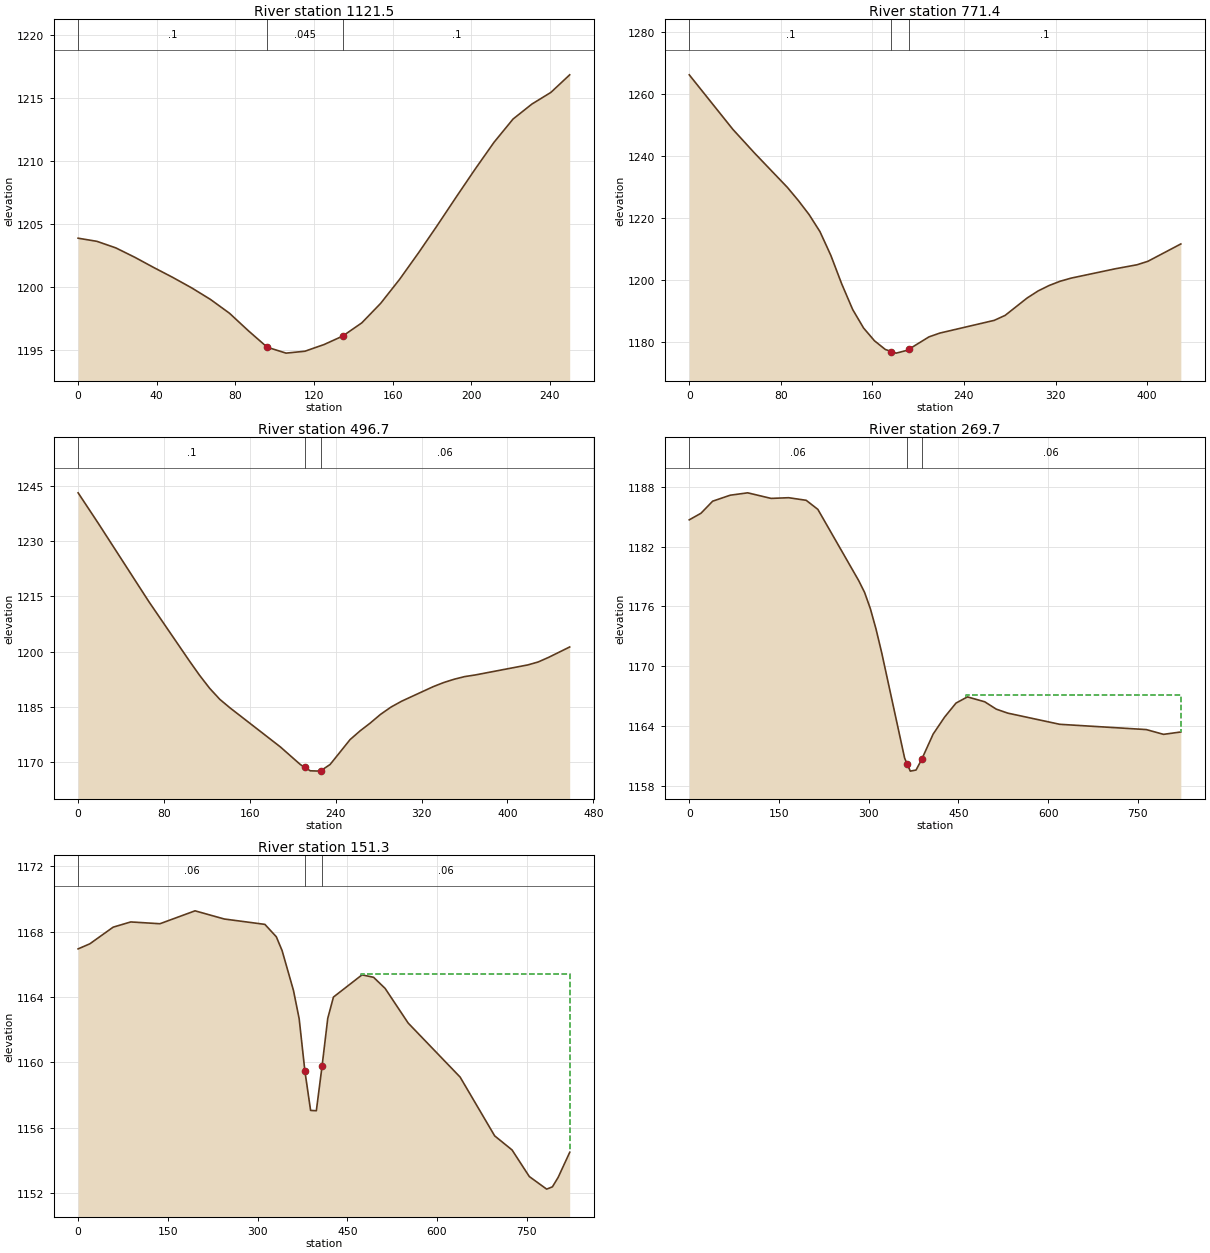
Type RM Length L Ch R = 1 ,1121.5  ,347.8,350.1,352.1
XS GIS Cut Line= 2
     1863944.667      326104.836     1863697.271      326141.729
#Sta/Elev= 29
       0 1203.86     9.6 1203.61    19.2 1203.09    28.9 1202.34    38.5 1201.53
    48.1 1200.75    57.7 1199.92    67.3    1199      77  1197.9    86.6 1196.51
    96.2  1195.2   105.8 1194.73   115.4 1194.88   120.3 1195.15   125.1 1195.41
   134.7 1196.09   135.3 1196.16   144.3 1197.13   153.9 1198.68   163.6  1200.6
   173.2  1202.7   182.8 1204.89   192.4 1207.14     202 1209.35   211.6 1211.48
   221.3 1213.33   230.9 1214.52   240.5 1215.44   250.1 1216.84
#Mann= 3 , 0 , 0
       0      .1       0    96.2    .045       0   134.7      .1       0
Bank Sta=96.2,134.7
XS Rating Curve= 0 ,0
Exp/Cntr=0.3,0.1

Type RM Length L Ch R = 1 ,771.4   ,280.3,274.6,268.8
XS GIS Cut Line= 3
     1863979.389      325766.295     1863703.781      325781.485
     1863569.233       325855.27
#Sta/Elev= 30
       0 1266.13    38.1 1248.55    57.1 1240.88    85.7 1229.85    95.2 1225.65
   104.7 1221.08   114.2 1215.57   123.7 1207.92   133.2 1198.72   142.8 1190.45
   152.3  1184.5   161.8 1180.39   171.3 1177.58   176.7 1176.91   180.8  1176.4
   190.4 1177.31   191.7 1177.61   209.4 1181.63   218.9 1182.86   266.5 1186.97
     276 1188.57   295.2 1194.17   304.8 1196.45   314.4  1198.2     324 1199.57
   333.6 1200.58   371.9 1203.57   391.1 1204.88   400.7    1206   429.5  1211.6
#Mann= 3 , 0 , 0
       0      .1       0   176.7    .045       0   191.7      .1       0
Bank Sta=176.7,191.7
XS Rating Curve= 0 ,0
Exp/Cntr=0.3,0.1

Type RM Length L Ch R = 1 ,496.7   ,230.5,227,223.5
XS GIS Cut Line= 4
     1863892.583       325534.09     1863723.313      325521.069
     1863625.656      325551.451     1863486.767      325675.149
#Sta/Elev= 30
       0 1243.02    18.9 1234.71      66 1213.49   103.8 1197.41   113.2 1193.55
   122.6 1190.02     132 1187.05   141.5 1184.74   188.4 1174.16     207 1169.39
     211 1168.65   216.3 1167.68   225.6 1167.59     226 1167.67   234.8  1169.4
   253.4 1176.14   262.8 1178.52     272 1180.58   281.8 1182.98   291.6 1184.97
   301.4 1186.54   330.8 1190.48   340.6  1191.6   350.4  1192.5   360.1 1193.21
   369.9 1193.65   418.9 1196.37   428.7 1197.18   438.4 1198.43     458 1201.24
#Mann= 3 , 0 , 0
       0      .1       0     211    .045       0     226     .06       0
Bank Sta=211,226
XS Rating Curve= 0 ,0
Exp/Cntr=0.3,0.1

Type RM Length L Ch R = 1 ,269.7   ,118.5,118.5,118.5
XS GIS Cut Line= 4
     1863849.723      325084.871       1863647.9      325297.545
      1863485.14       325377.84     1863137.918       325382.18
#Sta/Elev= 30
       0 1184.68    19.6 1185.34    39.1 1186.55    68.4 1187.15    97.7 1187.39
   136.8 1186.83   166.1  1186.9   195.5 1186.64     215 1185.73   283.4 1178.57
   293.2 1177.39   302.8 1175.76   312.3 1173.71   321.8 1171.33   360.1 1160.76
   364.2  1160.2   369.6 1159.46   379.2 1159.57   388.7 1160.65   407.8 1163.18
   426.9 1164.88     446 1166.29   465.1 1166.91     494 1166.42   513.3 1165.68
   532.6 1165.28   619.4 1164.16   764.1 1163.63     793 1163.15   821.9 1163.39
#Mann= 3 , 0 , 0
       0     .06       0   364.2    .045       0   388.7     .06       0
#XS Ineff= 2 , 0
                          463.38         1167.05
Permanent Ineff=
       F       F
Bank Sta=364.2,388.7
XS Rating Curve= 0 ,0
Exp/Cntr=0.3,0.1

Type RM Length L Ch R = 1 ,151.3   ,155.2,151.3,147.3
XS GIS Cut Line= 4
      1863806.32      324974.194     1863604.498      325186.867
     1863441.737      325267.163     1863094.515      325271.503
#Sta/Elev= 30
       0 1166.94    19.6 1167.25    58.6 1168.27      88 1168.59   136.8 1168.48
   195.5 1169.27   244.3 1168.77   312.3 1168.44   331.4 1167.68     341 1166.84
   360.1 1164.39   369.6 1162.66   379.2 1159.45   388.7 1157.05   398.3 1157.03
   407.8 1159.74   417.4 1162.69   426.9 1163.99   474.7 1165.35     494  1165.2
   513.3 1164.52   551.8  1162.4   638.7 1159.09   696.5 1155.49   725.5 1154.63
   754.4    1153   783.4 1152.23     793 1152.37   802.6 1152.95   821.9 1154.48
#Mann= 3 , 0 , 0
       0     .06       0   379.2    .045       0   407.8     .06       0
#XS Ineff= 2 , 0
                          473.24         1165.39
Permanent Ineff=
       F       F
Bank Sta=379.2,407.8
XS Rating Curve= 0 ,0
Exp/Cntr=0.3,0.1

Chan Stop Cuts=-1
Use User Specified Reach Order=0
Composite Channel Slope=5